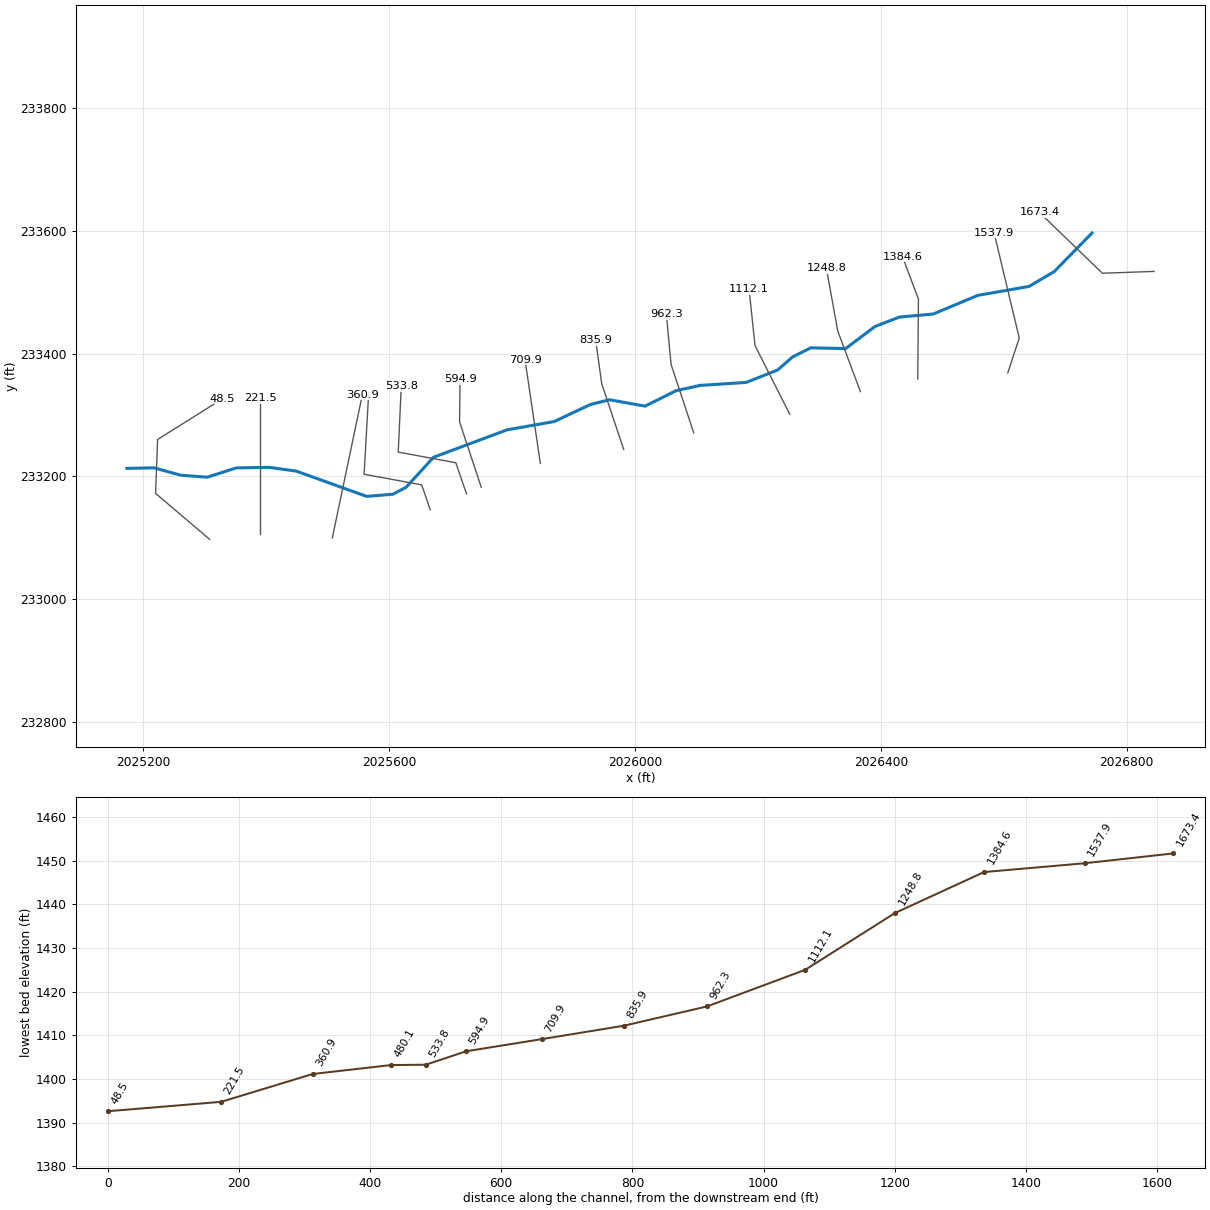
--- HWRDCK.prj (project) ---

Proj Title=HWRDCK
Current Plan=p01
Default Exp/Contr=0,0
English Units
Geom File=g01
Flow File=f01
Plan File=p01
BEGIN DESCRIPTION:
END DESCRIPTION:
DSS Export Rating Curves= 0
DSS Export Rating Curve Sorted= 0
DSS Export Volume Flow Curves= 0
DXF OffsetX= 0
DXF OffsetY= 0
DXF ScaleX= 0
DXF ScaleY= 0

--- HWRDCK.p01 (plan) ---

Plan Title=Floodplain
Program Version=4.00
Geom File=g01
Flow File=f01
K Sum by GR=0
Std Step Tol=0.01
Critical Tol=0.01
Num of Std Step Trials=20
Max Error Tol=0.3
Flow Tol Ratio=0.001
Split Flow NTrial=30
Split Flow Tol=0.02
Split Flow Ratio=0.02
Log Output Level=0
Friction Slope Method=1
Unsteady Friction Slope Method=2
Unsteady Bridges Friction Slope Method=1
Global Log Level=0
CheckData=False
Run HTab=0
Run UNet=0
Run PostProcess=0
UNET Theta=0
UNET Theta Warmup=0
UNET ZTol=0
UNET ZSATol=0
UNET MxIter=0
UNET MaxInSteps=0
UNET DtIC=0
UNET DtMin=0
UNET MaxCRTS=0
UNET WFStab=0
UNET SFStab=0
UNET WFX=0
UNET SFX=0
UNET DSS MLevel=0
UNET DZMax Abort=0
UNET Convert EG Bridges=0
UNET Use Existing IB Tables=0
UNET Froude Limit=0
UNET Froude Power=0
Write IC File=0
Echo Input=False
Echo Output=False
Write Detailed=0

--- HWRDCK.f01 (steady flow) ---

Flow Title=2010 USGS WV Regression Equation
Program Version=5.03
Number of Profiles= 1
Profile Names=P100yr
River Rch & RM=HWRDCK,Main            ,1673.4
521.5776
River Rch & RM=HWRDCK,Main            ,221.5
531.6224
Boundary for River Rch & Prof#=HWRDCK,Main            , 1
Up Type= 0
Dn Type= 3
Dn Slope=0.01224
DSS Import GetInterval= 0
DSS Import GetPeak= 0
DSS Import FillOption= 0

--- HWRDCK.g01 (geometry) ---

Geom Title=LiDAR
Program Version=4.10

River Reach=HWRDCK          ,Main
Reach XY= 30
     2026743.701      233597.003      2026682.31      233534.149
     2026641.338      233509.843     2026558.004       233495.26
     2026485.088      233464.791     2026430.227      233459.843
     2026390.643      233444.565     2026342.726      233408.455
     2026285.869       233409.67     2026256.286      233394.811
     2026231.972      233373.447     2026180.834      233353.246
     2026106.181      233348.472     2026066.685      233339.791
     2026016.338      233314.617     2025958.178      233325.034
     2025927.362      233317.222     2025868.334      233289.444
     2025791.945      233275.989     2025672.154      233231.284
     2025627.449      233182.239     2025605.747      233170.954
     2025563.213      233167.482     2025448.629      233208.715
     2025404.793      233214.791     2025351.407      233213.923
     2025303.665      233198.732     2025260.915      233201.957
     2025217.301      233214.041     2025173.348      233213.084

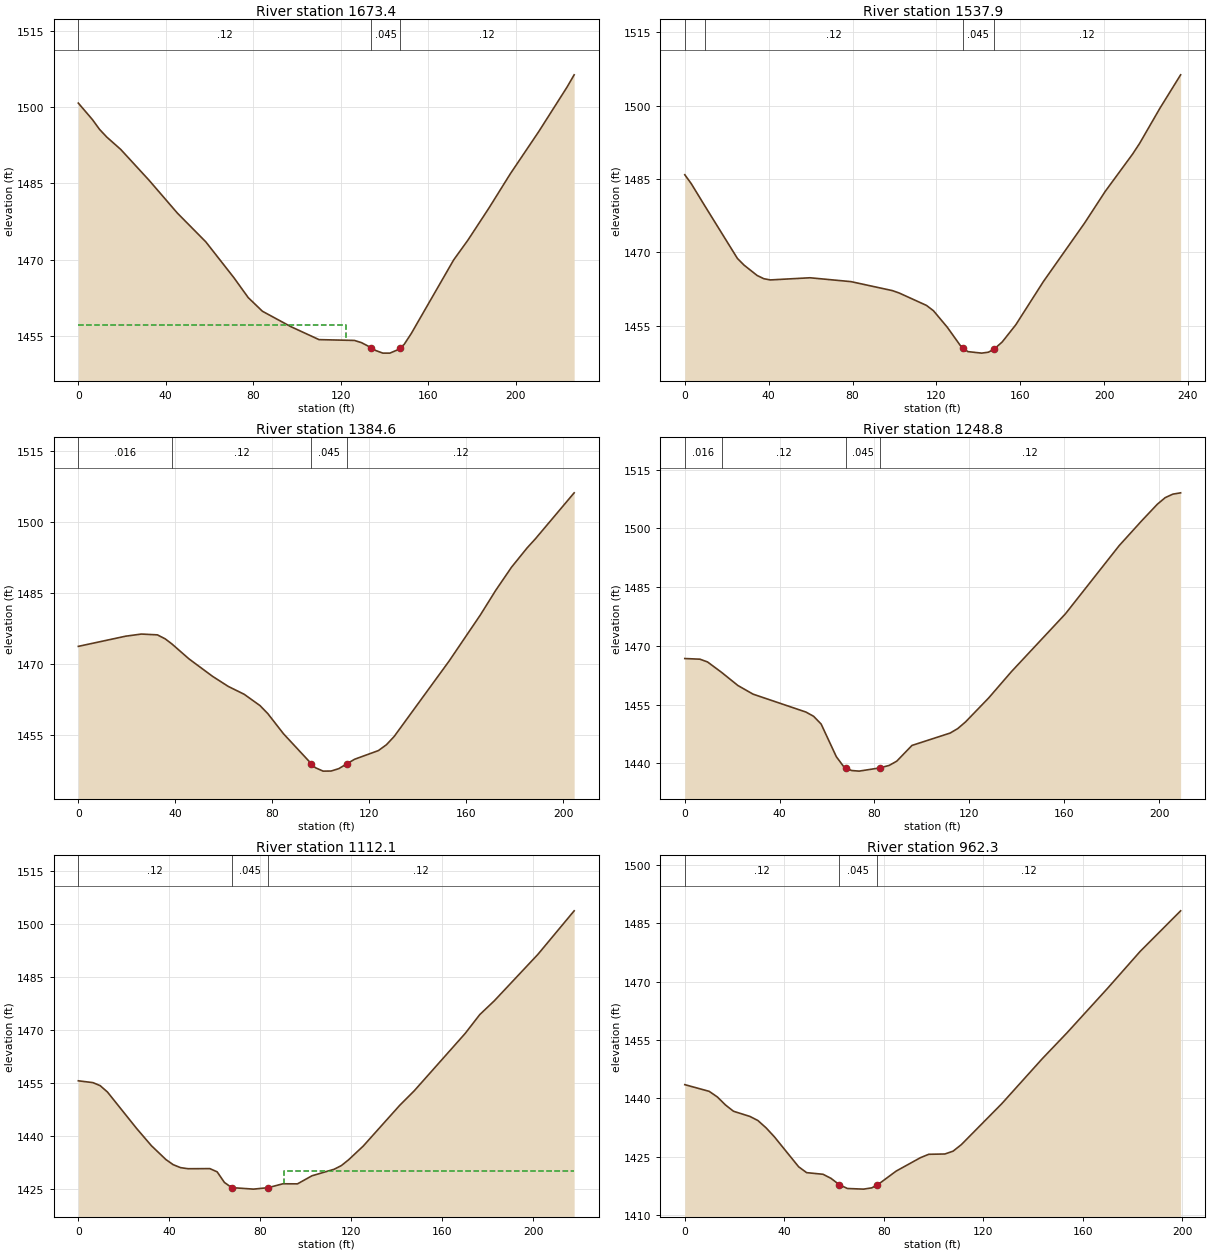
Type RM Length L Ch R = 1 ,1673.4  ,148.2,135.6,122.4
XS GIS Cut Line= 3
     2026844.607      233534.304     2026760.513      233531.327
     2026658.011      233630.523
#Sta/Elev= 30
       0 1500.76     6.5  1497.5     9.7 1495.61      13  1494.1    19.4 1491.67
    32.4  1485.6    45.3 1479.18    58.3 1473.54    71.2 1466.48    77.7  1462.6
    84.2 1459.92    97.1 1456.92   110.1 1454.35   126.3 1454.19   129.5 1453.76
  133.991452.761     136 1452.22   139.3  1451.7   142.5  1451.7   145.7 1452.28
  147.211452.788     149 1453.39   152.2 1455.48   171.7    1470   178.2 1473.87
   187.9 1480.22   197.6 1486.89   210.6 1495.17   223.6 1503.94   226.8 1506.31
#Mann= 3 ,-1 , 0
       0     .12       0  133.99    .045       0  147.21     .12       0
#XS Ineff= 2 , 0
          122.29  1457.3
Permanent Ineff=
       F       F
Bank Sta=133.99,147.21
XS Rating Curve= 0 ,0
Exp/Cntr=0.3,0.1

Type RM Length L Ch R = 1 ,1537.9  ,158.2,153.2,147.2
XS GIS Cut Line= 3
      2026606.57      233368.882     2026625.241      233425.554
      2026584.21      233597.583
#Sta/Elev= 30
       0 1485.87     3.1 1484.04    9.551479.518    25.1 1468.78    28.3  1467.4
    34.5  1465.3    37.7 1464.64    40.8 1464.39    59.7 1464.83    79.3 1464.04
      99 1462.21   102.2 1461.73   115.3 1459.18   118.6  1458.1   125.2 1454.73
   131.7 1450.83   132.5 1450.57     135 1449.75   141.6 1449.44   144.8 1449.63
   147.5 1450.24   151.4 1451.72   157.9 1455.24     171 1464.03   190.7 1476.01
   200.5 1482.45   213.6  1490.1   216.9 1492.25   226.7 1499.51   236.5 1506.28
#Mann= 4 ,-1 , 0
       0    .016       0    9.55     .12       0   132.5    .045       0
   147.5     .12       0
Bank Sta=132.5,147.5
XS Rating Curve= 0 ,0
Exp/Cntr=0.3,0.1

Type RM Length L Ch R = 1 ,1384.6  ,127.1,135.9,143.7
XS GIS Cut Line= 3
     2026460.093      233358.946     2026461.179      233489.154
     2026435.137      233558.599
#Sta/Elev= 30
       0 1473.78    19.5 1475.93      26 1476.38    32.6 1476.21    35.8 1475.37
   38.521474.315    45.6 1471.14    55.3 1467.46    61.8 1465.32    68.4 1463.65
    74.9 1461.26    78.1 1459.58    84.6  1455.3   96.04 1448.99    97.7 1448.15
   100.9 1447.42   104.2 1447.44   107.4 1447.95   110.7 1448.97   113.9 1449.93
   123.7 1451.76     127 1452.99   130.2 1454.74   152.8 1470.64   165.7 1480.39
   172.1 1485.64   178.6 1490.52     185 1494.58   188.3 1496.43   204.4 1506.22
#Mann= 4 ,-1 , 0
       0    .016       0   38.52     .12       0   96.04    .045       0
   110.7     .12       0
Bank Sta=96.04,110.7
XS Rating Curve= 0 ,0
Exp/Cntr=0.3,0.1

Type RM Length L Ch R = 1 ,1248.8  ,132.9,136.6,138.2
XS GIS Cut Line= 3
     2026366.778      233338.329     2026329.885      233437.071
     2026311.439      233539.067
#Sta/Elev= 30
       0 1466.77     6.4  1466.6     9.6 1465.89   15.511463.239    22.4 1459.88
    28.8 1457.67    51.1  1453.1    54.3 1452.03    57.5 1450.04    63.9 1441.71
    67.1  1439.1   68.181438.789    70.3 1438.18    73.5 1438.02    82.2 1438.84
    86.2 1439.48    89.4 1440.57    95.8 1444.58   111.9 1447.74   115.1 1448.88
   118.4 1450.59   128.1 1456.67   137.8 1463.46   160.5 1478.17   183.2 1495.61
   192.9 1502.08   199.3 1506.18   202.6 1507.85   205.8 1508.74   209.1 1509.08
#Mann= 4 ,-1 , 0
       0    .016       0   15.51     .12       0   68.18    .045       0
    82.2     .12       0
Bank Sta=68.18,82.2
XS Rating Curve= 0 ,0
Exp/Cntr=0.3,0.1

Type RM Length L Ch R = 1 ,1112.1  ,152.8,149.8,146
XS GIS Cut Line= 3
      2026251.76      233301.437     2026195.337      233413.199
     2026185.571       233505.43
#Sta/Elev= 30
       0 1455.65     6.4 1455.14     9.6 1454.28    12.8 1452.48    25.7 1442.11
    32.1 1437.31    38.5 1433.38    41.7 1431.93    44.9  1431.1    48.2 1430.79
    57.8 1430.82      61 1429.91    64.2 1426.91    67.4 1425.45      77 1425.02
    83.5 1425.44    89.9 1426.53    96.3 1426.51   102.7  1428.8   112.4 1430.63
   115.6 1431.68   118.8 1433.33   125.2 1437.19   141.2 1448.69   147.6 1452.81
     170 1469.04   176.4 1474.36   182.8 1478.27     202 1491.43   217.9 1503.72
#Mann= 3 ,-1 , 0
       0     .12       0    67.4    .045       0    83.5     .12       0
#XS Ineff= 2 , 0
                           90.56         1430.14
Permanent Ineff=
       F       F
Bank Sta=67.4,83.5
XS Rating Curve= 0 ,0
Exp/Cntr=0.3,0.1

Type RM Length L Ch R = 1 ,962.3   ,126.2,126.4,125.1
XS GIS Cut Line= 3
      2026095.51      233271.055     2026058.618      233382.817
     2026051.022      233464.198
#Sta/Elev= 30
       0  1443.5     9.8 1441.78    13.1 1440.33    16.4 1438.25    19.6 1436.65
    26.2 1435.32    29.4 1434.27    32.7 1432.38      36  1430.1    45.8 1422.36
      49 1420.86    55.6 1420.44    58.8 1419.39    62.1 1417.78    65.4 1416.78
    71.9 1416.62    75.2 1416.95   77.491417.706      85 1421.26    94.8 1424.72
    98.1 1425.58   104.6 1425.66   107.9 1426.39   111.2 1428.06   127.5 1438.62
   143.8  1450.2   153.7 1456.83     170 1468.27   183.1 1477.76   199.4 1488.22
#Mann= 3 ,-1 , 0
       0     .12       0    62.1    .045       0   77.49     .12       0
Bank Sta=62.1,77.49
XS Rating Curve= 0 ,0
Exp/Cntr=0.3,0.1

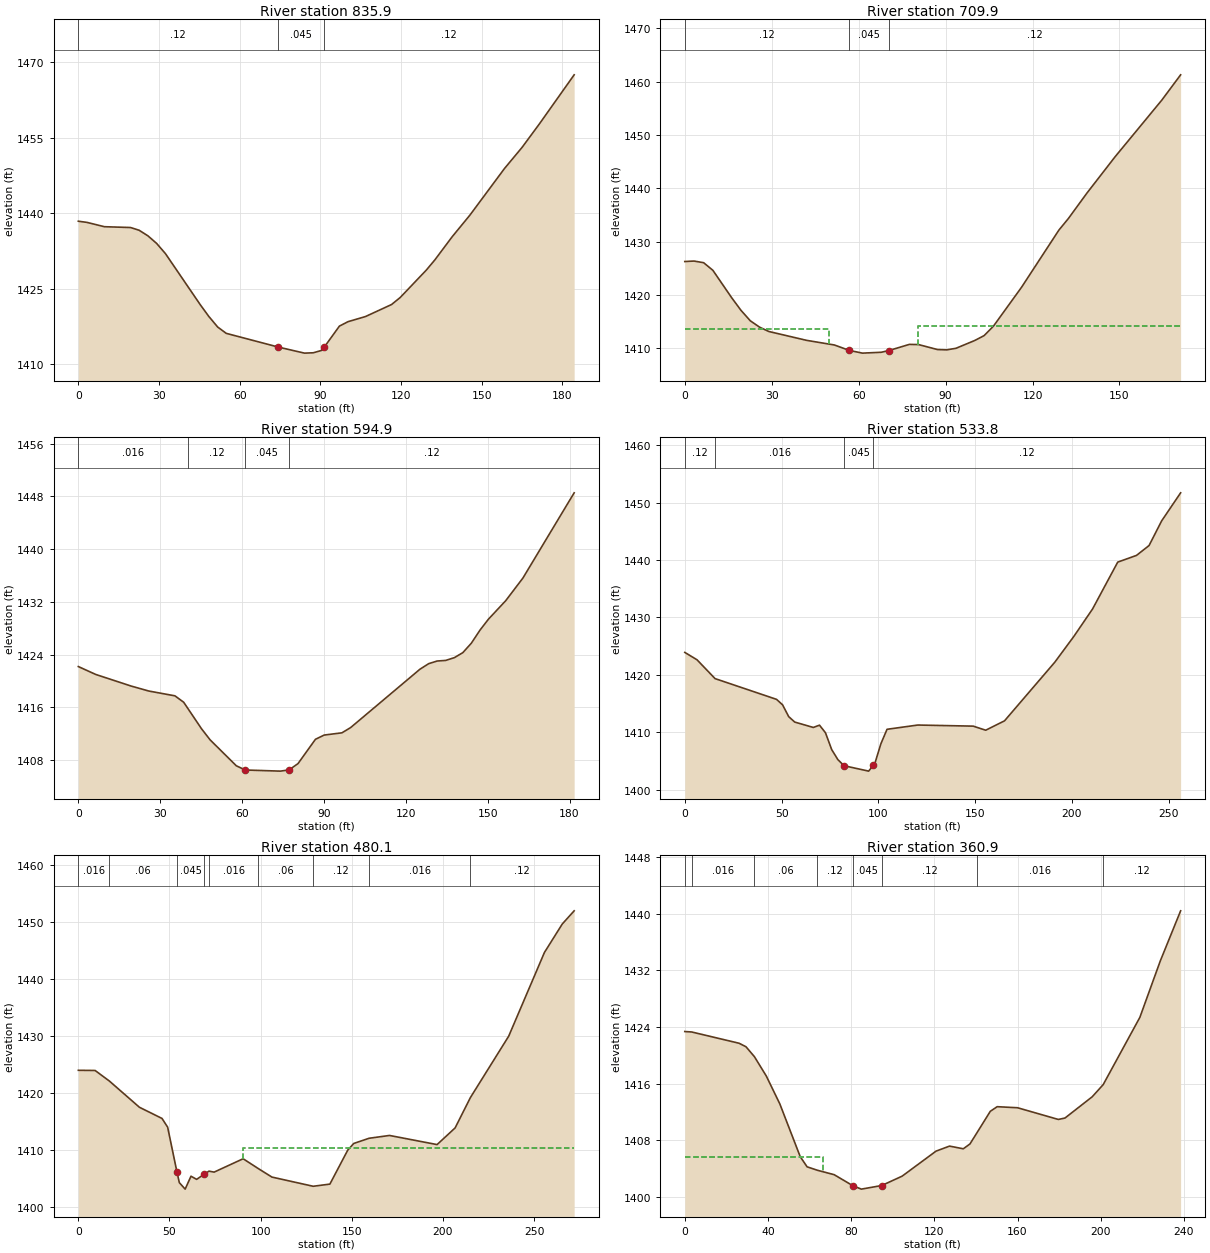
Type RM Length L Ch R = 1 ,835.9   ,129.7,126,121.8
XS GIS Cut Line= 3
     2025981.578      233243.928     2025945.771       233351.35
     2025936.005       233421.88
#Sta/Elev= 30
       0 1438.42     3.2 1438.19     9.7 1437.33    19.4 1437.17    22.6 1436.63
    25.9 1435.51    29.1 1434.02    32.4 1431.98    45.3 1421.87    48.5 1419.52
    51.8 1417.41      55 1416.14    74.4 1413.41    84.1 1412.21    87.4 1412.28
    90.6 1412.77   91.43 1413.38    97.1 1417.58   100.3 1418.46   106.8 1419.48
   116.5 1421.87   119.7 1423.26   129.4  1428.7   132.6 1430.74   139.1 1435.38
   145.6 1439.61   158.5  1448.9     165 1453.07   171.5 1457.78   184.4 1467.51
#Mann= 3 ,-1 , 0
       0     .12       0    74.4    .045       0   91.43     .12       0
Bank Sta=74.4,91.43
XS Rating Curve= 0 ,0
Exp/Cntr=0.3,0.1

Type RM Length L Ch R = 1 ,709.9   ,110.9,115.1,118.6
XS GIS Cut Line= 2
     2025845.944      233221.142     2025820.988      233390.413
#Sta/Elev= 30
       0 1426.29     3.2 1426.38     6.5 1426.07     9.7 1424.64    16.1 1419.56
    19.4 1417.13    22.6 1415.18    25.8 1413.98      29 1413.17      42 1411.51
    51.6 1410.64    56.81409.616    61.3 1409.11    67.8 1409.27    70.4 1409.59
    77.5 1410.75    80.7 1410.71    87.2 1409.78    90.4 1409.72    93.6 1410.02
   100.1 1411.49   103.3  1412.4   106.5 1414.16   116.2 1421.46   129.1 1432.19
   132.4 1434.38   138.8 1439.15   148.5 1445.95   164.6 1456.56   171.1 1461.31
#Mann= 3 ,-1 , 0
       0     .12       0    56.8    .045       0    70.4     .12       0
#XS Ineff= 2 , 0
           49.78 1413.72   80.43         1414.19
Permanent Ineff=
       F       F
Bank Sta=56.8,70.4
XS Rating Curve= 0 ,0
Exp/Cntr=0.3,0.1

Type RM Length L Ch R = 1 ,594.9   ,26.7,61.1,86.9
XS GIS Cut Line= 3
     2025749.819      233182.034       2025714.5      233288.998
     2025715.237      233358.078
#Sta/Elev= 30
       0 1422.19     6.4 1420.99    19.3 1419.24    25.8 1418.48    35.4 1417.75
    38.6 1416.78   40.141415.837    45.1 1412.78    48.3 1411.07    57.9 1407.14
    61.2  1406.5      74 1406.33    77.2 1406.51    80.5 1407.47    86.9 1411.16
    90.1  1411.8    96.6 1412.14    99.8 1412.94   125.2 1421.79   128.4 1422.63
   131.5 1423.03   134.6 1423.12   137.8 1423.54   140.9  1424.3     144 1425.72
   147.2 1427.72   150.3 1429.38   156.6 1432.17   162.9  1435.6   181.7 1448.54
#Mann= 4 ,-1 , 0
       0    .016       0   40.14     .12       0    61.2    .045       0
    77.2     .12       0
Bank Sta=61.2,77.2
XS Rating Curve= 0 ,0
Exp/Cntr=0.3,0.1

Type RM Length L Ch R = 1 ,533.8   ,69.2,53.7,56.3
XS GIS Cut Line= 4
     2025725.811      233171.527      2025708.43      233222.299
      2025614.68      233239.661     2025619.635      233346.701
#Sta/Elev= 30
       0 1423.92     6.3 1422.64   15.641419.361    47.4 1415.75    50.5 1414.81
    53.7 1412.74    56.8  1411.8    66.4 1410.86    69.6 1411.26    72.7 1409.93
    75.9 1407.01    79.1 1405.26    82.3  1404.2      95 1403.26   97.481404.291
    98.2 1404.59   101.3    1408   104.5 1410.54   120.4 1411.28     149 1411.09
   155.5 1410.38   165.2 1412.01   191.2 1422.22     201 1426.69   210.7 1431.48
   223.7 1439.63   233.4  1440.8   239.9 1442.52   246.4 1446.81   256.2 1451.69
#Mann= 4 ,-1 , 0
       0     .12       0   15.64    .016       0    82.3    .045       0
   97.48     .12       0
Bank Sta=82.3,97.48
XS Rating Curve= 0 ,0
Exp/Cntr=0.3,0.1

Type RM Length L Ch R = 1 ,480.1   ,149.3,119.2,77.9
XS GIS Cut Line= 4
     2025666.701      233145.798     2025652.874      233186.188
     2025559.124      233203.549     2025566.675      233337.311
#Sta/Elev= 30
       0 1423.98     9.2 1423.95   17.051422.096    33.5 1417.51    45.9 1415.55
      49 1414.02    54.1 1406.17    55.4 1404.31    58.6 1403.17    61.8 1405.43
    64.9 1404.88    69.1  1405.8   71.681406.317    74.5 1406.15    90.4 1408.49
   98.791406.756   106.2 1405.28  128.83 1403.67     138 1404.05   147.8    1410
   151.1 1411.17  159.491412.076   170.7 1412.57   196.8 1410.97   206.7 1413.89
  215.091419.209   236.1 1429.96   255.7 1444.62   265.5 1449.61     272 1451.91
#Mann= 9 ,-1 , 0
       0    .016       0   17.05     .06       0    54.1    .045       0
    69.1     .12       0   71.68    .016       0   98.79     .06       0
  128.83     .12       0  159.49    .016       0  215.09     .12       0
#XS Ineff= 2 , 0
                           90.09         1410.34
Permanent Ineff=
       F       F
Bank Sta=54.1,69.1
XS Rating Curve= 0 ,0
Exp/Cntr=0.3,0.1

Type RM Length L Ch R = 1 ,360.9   ,134.7,139.4,144
XS GIS Cut Line= 2
     2025507.403      233099.614     2025556.231      233332.904
#Sta/Elev= 30
       0 1423.35    3.31 1423.29    26.1  1421.7    29.4 1421.21   33.481419.806
    39.2 1417.07    45.7 1413.14    55.5  1405.7    58.8 1404.27   63.66 1403.79
    71.8 1403.16   80.781401.607    84.9 1401.12    94.7 1401.63   104.5 1402.95
   120.8 1406.48   127.3 1407.19   133.9 1406.81   137.1 1407.49  140.551409.108
   146.9  1412.1   150.2 1412.75     160  1412.6   179.6 1410.95   182.8 1411.15
   195.9 1414.15  201.16 1415.86   218.8 1425.35   228.6 1433.29   238.4 1440.38
#Mann= 8 ,-1 , 0
       0     .08       0    3.31    .016       0   33.48     .06       0
   63.66     .12       0   80.78    .045       0    94.7     .12       0
  140.55    .016       0  201.16     .12       0
#XS Ineff= 2 , 0
           66.31 1405.66
Permanent Ineff=
       F       F
Bank Sta=80.78,94.7
XS Rating Curve= 0 ,0
Exp/Cntr=0.3,0.1

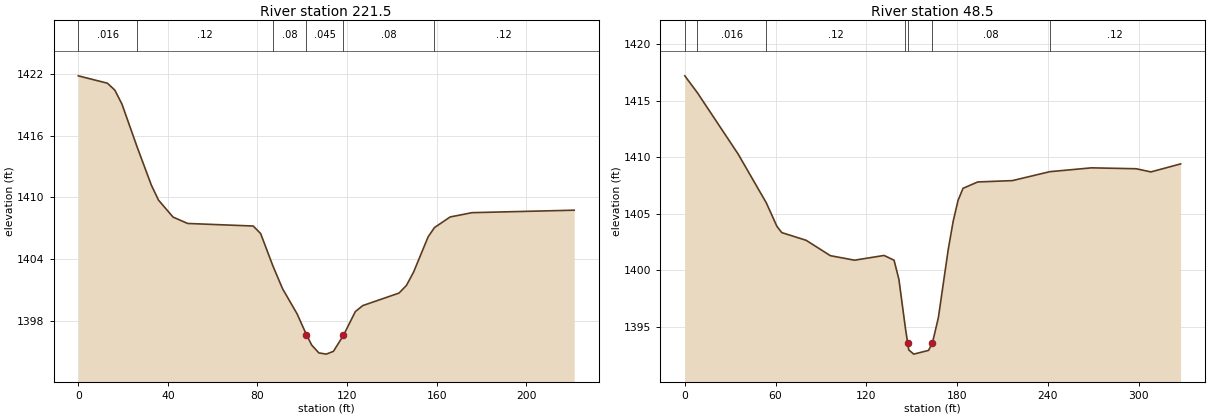
Type RM Length L Ch R = 1 ,221.5   ,173.4,173,171.7
XS GIS Cut Line= 2
     2025390.215      233106.125     2025390.215      233327.479
#Sta/Elev= 30
       0 1421.81      13 1421.09    16.3 1420.42    19.5 1419.05   26.261414.886
    32.6 1411.18    35.8 1409.72    42.3 1408.07    48.8 1407.45    78.1  1407.2
    81.4 1406.47   86.861403.332    91.2  1401.1    97.7 1398.65  101.861396.634
   104.2 1395.62   107.4 1394.86   110.7 1394.74   113.9 1395.01  118.36 1396.56
   123.7 1398.88     127 1399.46   143.2 1400.68   146.5 1401.42   149.7 1402.72
   156.2 1406.15  159.03 1407.05     166 1408.08   175.8  1408.5   221.4 1408.74
#Mann= 6 ,-1 , 0
       0    .016       0   26.26     .12       0   86.86     .08       0
  101.86    .045       0  118.36     .08       0  159.03     .12       0
Bank Sta=101.86,118.36
XS Rating Curve= 0 ,0
Exp/Cntr=0.3,0.1

Type RM Length L Ch R = 1 ,48.5    ,43.8,48.5,53.2
XS GIS Cut Line= 4
      2025307.75      233097.444     2025219.859      233172.314
     2025223.114      233260.204     2025328.366      233326.394
#Sta/Elev= 30
       0 1417.21    8.331415.714    35.3 1410.28   53.881405.971    60.9 1403.89
    64.1 1403.34    80.2 1402.66    96.2  1401.3   112.2  1400.9   131.7 1401.32
   138.3  1400.9   141.5 1399.21  145.861394.843  147.271393.609     148 1392.97
   151.3 1392.59   161.1 1392.92   163.7  1393.6   167.6 1395.82   174.1 1401.84
   177.4 1404.36   180.6 1406.19   183.9 1407.26   193.6 1407.82   216.5 1407.94
  241.22 1408.73   268.8 1409.07   298.3 1408.99   308.1 1408.71   327.7 1409.42
#Mann= 7 ,-1 , 0
       0     .06       0    8.33    .016       0   53.88     .12       0
  145.86     .08       0  147.27    .045       0   163.7     .08       0
  241.22     .12       0
Bank Sta=147.27,163.7
XS Rating Curve= 0 ,0
Exp/Cntr=0.3,0.1

Chan Stop Cuts=-1
Use User Specified Reach Order=0
Composite Channel Slope=5